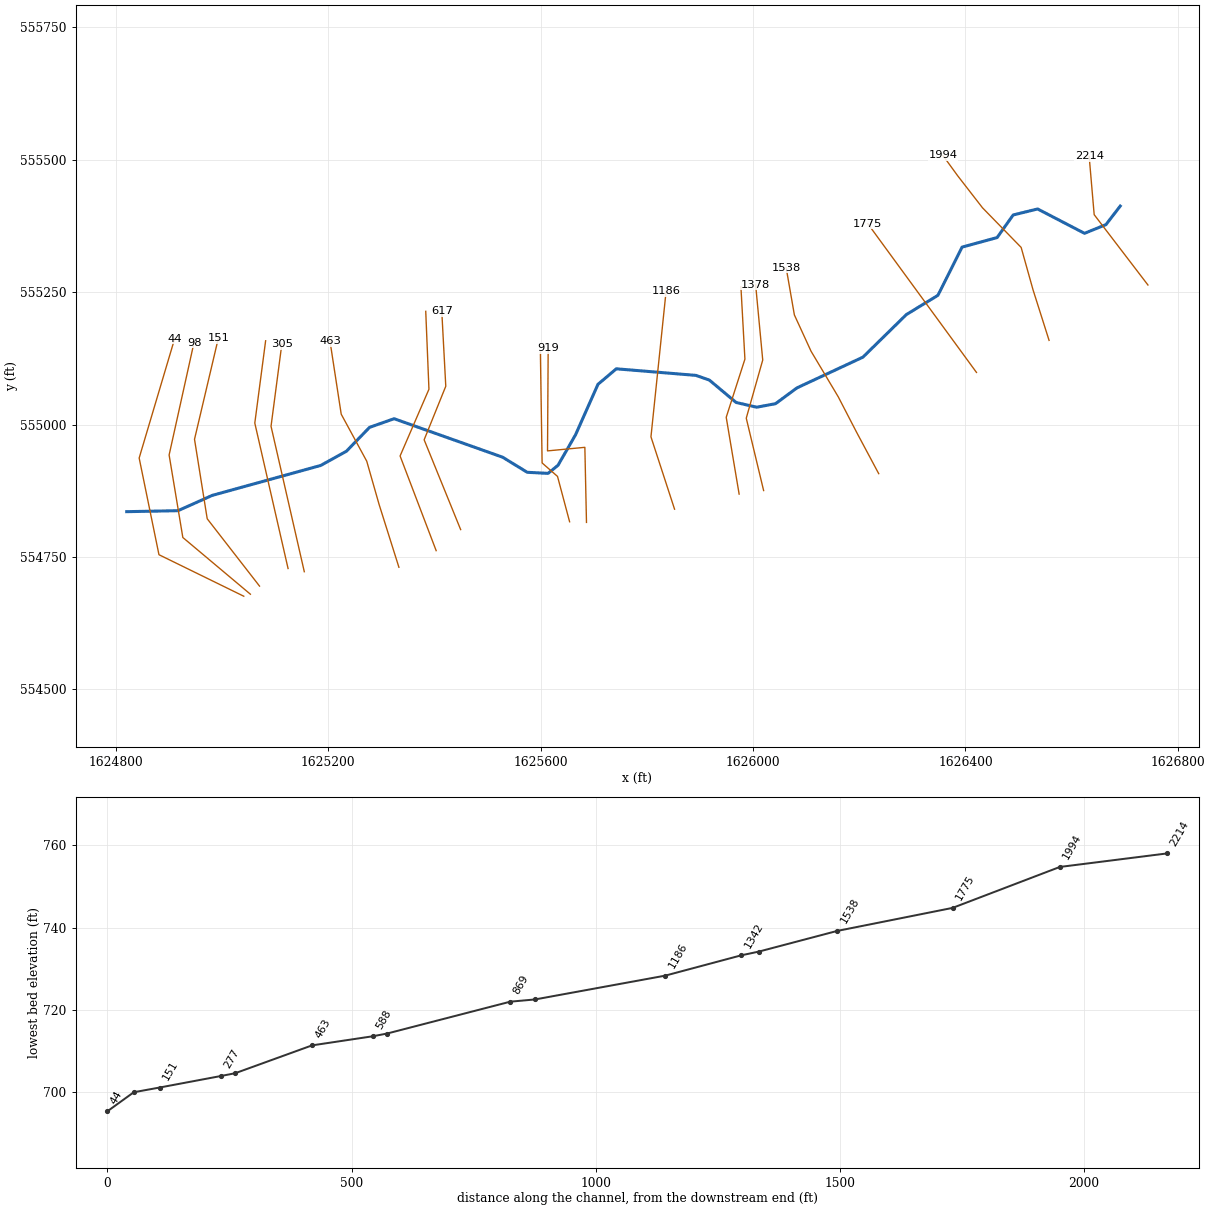
--- BrownsRn.prj (project) ---

Proj Title=BrownsRn
Current Plan=p01
Default Exp/Contr=0,0
English Units
Geom File=g01
Flow File=f01
Plan File=p01
BEGIN DESCRIPTION:
---------- MODELED AS PART OF WVEM CTP PROGRAM, 2025----------
Stream Name: Browns Run
Flood Zone: AFH
Marshall County, WV
HEC-RAS Version: RAS 6.6
Vertical Datum: NAVD88
Projection: NAD 1983 StatePlane West Virginia N FIPS 4701 (US Feet)
Terrain: 1-meter West Virginia FEMA R3 South Central (collected 2018-2019)
Land Use: 2024 NLCD
Hydrologic Method:
Duda et al., "Estimation of magnitude and frequency of floods for rural, unregulated streams in and near Virginia and West Virginia." September 8, 2025.
Additional Model Notes:
None
END DESCRIPTION:
DSS Export Rating Curves= 0
DSS Export Rating Curve Sorted= 0
DSS Export Volume Flow Curves= 0
DXF OffsetX= 0
DXF OffsetY= 0
DXF ScaleX= 0
DXF ScaleY= 0

--- BrownsRn.p01 (plan) ---

Plan Title=Floodplain
Program Version=6.60
Short Identifier=Floodplain
Geom File=g01
Flow File=f01
Subcritical Flow
K Sum by GR= 0
Std Step Tol= 0.01
Critical Tol= 0.01
Num of Std Step Trials= 20
Max Error Tol= 0.3
Flow Tol Ratio= 0.001
Split Flow NTrial= 30
Split Flow Tol= 0.02
Split Flow Ratio= 0.02
Log Output Level= 0
Friction Slope Method= 1
Unsteady Friction Slope Method= 2
Unsteady Bridges Friction Slope Method= 1
Parabolic Critical Depth
Global Vel Dist= 0 , 0 , 0
Global Log Level= 0
CheckData=False
Encroach Param=-1 ,0,0, 0
Flow Ratio Tolerance=0.1
Flow Ratio Min Ratio=0.5
Flow Ratio Max Ratio=4
Flow Ratio Max Iterations= 10
Mapping Interval=1HOUR
Computation Time Step Use Courant=        0
Computation Time Step Use Time Series=    0
Computation Time Step Count To Double=0
Computation Time Step Max Doubling=0
Computation Time Step Max Halving=0
Computation Time Step Residence Courant=0
Run HTab= 0
Run UNet= 0
Run Sediment= 0
Run PostProcess= 0
Run WQNet= 0
Run RASMapper=-1
UNET Theta= 0
UNET Theta Warmup= 0
UNET ZTol= 0
UNET ZSATol= 0
UNET MxIter= 0
UNET Max Iter WO Improvement= 0
UNET MaxInSteps= 0
UNET DtIC= 0
UNET DtMin= 0
UNET MaxCRTS= 0
UNET WFStab= 0
UNET SFStab= 0
UNET WFX= 1
UNET SFX= 1
UNET Gravity=32.17405
UNET 1D Methodology=Finite Difference
UNET DSS MLevel= 1
UNET Pardiso=0
UNET DZMax Abort= 0
UNET Use Existing IB Tables= 0
UNET Froude Reduction=False
UNET Froude Limit= 0
UNET Froude Power= 0
UNET D1 Cores= 0
UNET WindReference=Eulerian
UNET WindDragFormulation=Hsu (1988)
UNET D2 Coriolis=0
UNET D2 Cores= 0
UNET D2 Theta= 1
UNET D2 Theta Warmup= 1
UNET D2 Z Tol= 0.01
UNET D2 Volume Tol= 0.01
UNET D2 Max Iterations= 20
UNET D2 Advanced Convergence=0
UNET D2 WS Max Tol=0.15
UNET D2 WS RMS Tol=0.002
UNET D2 WS Stall Tol=1
UNET D2 Equation= 0
UNET D2 RampUpFraction=0.1
UNET D2 TimeSlices= 1
UNET D2 Turbulence Formulation=Non-Conservative (original)
UNET D2 Eddy Viscosity=0.3
UNET D2 Transverse Eddy Viscosity=0.1
UNET D2 Smagorinsky Mixing=0
UNET D2 BCVolumeCheck=0
UNET D2 Cores=0
UNET D2 SolverType=PARDISO (Direct)
UNET D2 Minimum Iterations= 3
UNET D2 Maximum Iterations= 30
UNET D2 Restart Number= 10
UNET D2 Relaxation Coeff=1.3
UNET D2 SOR Precondition Iterations= 10
UNET D2 ILUT Maximum Fill= 8
UNET D2 ILUT Tolerance=1E-08
UNET D2 Convergence Tolerance=0.00001
PS Theta= 1
PS WS Tol= 0.01
PS Volume Tol= 0.01
PS Max Iterations= 20
PS Equation= 0
PS Advance Time Step=-1
PS Target Courant=0.9
PS Time Slices= 1
PS Iterate With 2D=0
PS Project Initial WSE from DS=-1
PS Ramp Up Initial WSE from US=-1
PS Cores=0
UNET D1D2 MaxIter= 0
UNET D1D2 ZTol=0.01
UNET D1D2 QTol=0.1
UNET D1D2 MinQTol=1
Write IC File= 0
Write IC File at Fixed DateTime=0
Write IC File at Sim End=0
Echo Input=False
Echo Parameters=False
Echo Output=False
Write Detailed= 0
HDF Write Warmup=0
HDF Write Time Slices=0
HDF Flush=0
HDF Compression= 1
HDF Chunk Size= 1
HDF Spatial Parts= 1
HDF Use Max Rows=0
HDF Fixed Rows= 1
Calibration Method= 0
Calibration Iterations= 20
Calibration Max Change=0.05
Calibration Tolerance=0.2
Calibration Maximum=1.5
Calibration Minimum=0.5
Calibration Optimization Method= 1
WQ AD Non Conservative
WQ ULTIMATE=-1
WQ Max Comp Step=1HOUR
WQ Output Interval=15MIN
WQ Output Selected Increments= 0
WQ Create Restart=0
WQ Fixed Restart=0
WQ System Summary=0
WQ Write To DSS=0
Sorting and Armoring Iterations= 10
XS Update Threshold= 0.02
Bed Roughness Predictor= 0
Processes Affected by Predictor=Sediment Only
Hydraulics Update Threshold= 0.02
Energy Slope Method= 1
Volume Change Method= 1
Sediment Retention Method= 0
Sediment TS Multiplier= 1
Warm Up Method= 0
XS Weighting Method= 0
Number of US Weighted Cross Sections= 1
Number of DS Weighted Cross Sections= 1
Upstream XS Weight=0
Main XS Weight=1
Downstream XS Weight=0
Number of DS XS's Weighted with US Boundary= 1
Upstream Boundary Weight= 1
Weight of XSs Associated with US Boundary= 0
Number of US XS's Weighted with DS Boundary= 1
Downstream Boundary Weight= 0.5
Weight of XSs Associated with DS Boundary= 0.5
Percentile Method= 0
Sediment Output Level= 3
Mass or Volume Output= 0
Output Increment Type= 1
Profile and TS Output Increment= 1
Transport Output Increment 1
XS Output Flag= 0
XS Output Increment= 10
Read HDF5 Sediment Hotstart= 0
Sediment Hotstart Type= 0
Write Gradation File= 0
Read Gradation Hotstart= 0
Write HDF5 File= 1
Write Binary Output= 1
Write DSS Sediment File= 0
DSS Sediment Output Type= 1
SV Curve= 0
Specific Gage Flag= 0
Subcell Erosion Methods= 0
Subcell Deposition Methods= 0
Advection Scheme= 1
Matrix Solver= 0
Implicit Weighting Factor= 1
Maximum Outer Loop Convergence Iterations= 5
Convergence Maximum Absolute= 0.001
Convergence RMSE= 0.0001
Grain Fractions Max Abs Error= 0.001
Max Subgrid Regions= 1
Max Subgrid Length Scale= 3.402823E+38
Initial Layer Thickness= 3
Min Layer Thickness= 0.1
Max Layer Thickness= 6
Number of Layers= 5

--- BrownsRn.f01 (steady flow) ---

Flow Title=Flow
Program Version=6.60
Number of Profiles= 1
Profile Names=P100yr
River Rch & RM=BrownsRn,Main,2214
     703
Boundary for River Rch & Prof#=BrownsRn,Main            , 1
Up Type= 0
Dn Type= 3
Dn Slope=0.02
DSS Import GetInterval= 0
DSS Import GetPeak= 0
DSS Import FillOption= 0

--- BrownsRn.g01 (geometry) ---

Geom Title=Geometry
Program Version=6.60

River Reach=BrownsRn        ,Main
Reach XY= 30
     1626691.292       555412.74     1626664.466      555377.764
     1626624.057      555361.294     1626535.767      555407.306
     1626489.755      555395.931     1626459.533      555353.314
     1626393.584      555335.231     1626348.068      555244.173
     1626288.643      555207.828     1626206.933      555127.445
     1626082.776      555069.431     1626042.367      555039.548
     1626006.881      555032.926      1625968.24      555041.818
     1625917.743      555084.202     1625892.445      555093.031
     1625742.672      555105.426     1625708.184      555076.243
     1625666.002      554981.004     1625632.841      554923.123
     1625614.164      554907.963     1625574.944      554910.001
     1625528.592      554938.525     1625324.338      555011.194
     1625278.156      554994.894     1625234.521      554949.731
     1625186.132      554922.905     1624981.878      554866.366
     1624917.529      554837.502     1624820.997      554835.648

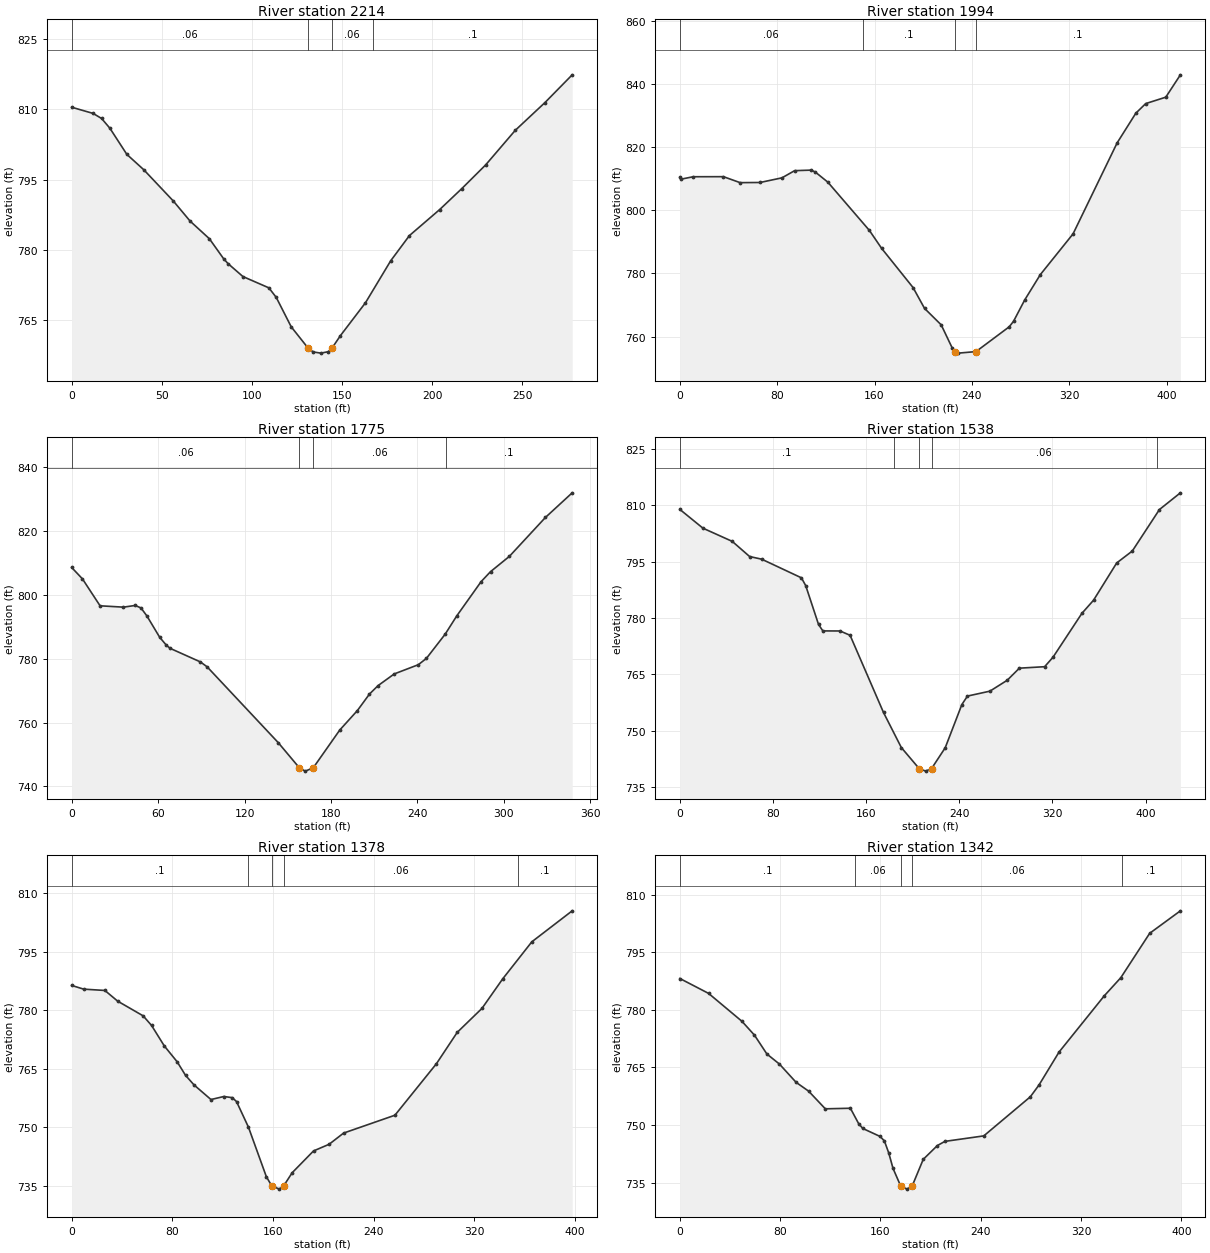
Type RM Length L Ch R = 1 ,2214    ,219.6,220,221.5
XS GIS Cut Line= 3
1626743.46334452555263.7061621361626642.25223193555396.518355708
1626632.80165479 555506.82654108
#Sta/Elev= 30
       0  810.46    11.9  809.14    16.6  808.06    21.2  805.98    30.6  800.41
      40  797.13    56.4  790.46    65.7  786.18    76.4  782.42    84.4   778.1
    86.8   777.1      95  774.36   109.4  771.95   113.5  769.91   121.8  763.64
   131.3  759.04   134.1  758.27   138.3  758.03   142.4  758.34  144.33  759.04
   149.1  761.76     163  768.77     177  777.72   187.4   783.1   204.2  788.65
   216.5  793.13   229.7  798.17   246.1  805.53   262.6  811.46   277.7  817.37
#Mann= 4 ,-1,0
       0     .06       0   131.3    .045       0  144.33     .06       0
  166.98      .1       0
Bank Sta=131.3,144.33
XS Rating Curve= 0 ,0
Exp/Cntr(USF)=0,0
Exp/Cntr=0.3,0.1

Type RM Length L Ch R = 1 ,1994    ,218.4,219.6,217.7
XS GIS Cut Line= 6
1626557.33369556555159.1357140541626527.12050138555254.671612233
1626504.78065105555334.6527514761626432.02948423555409.483966649
1626385.44230706555469.7676387281626357.50876296555508.289565163
#Sta/Elev= 30
       0  810.44     1.3  809.87      11  810.61    35.8  810.63    49.5  808.74
    65.9  808.79    83.9  810.26    94.3  812.53   107.9  812.71   111.3   812.1
   121.6   808.9   155.8  793.59   165.8  787.94   191.7  775.49   201.1  768.91
   214.8  763.69   223.9  756.33  226.49755.2245   228.9  754.74  243.39755.2235
   270.7  763.08   274.3  764.85   283.4  771.56   296.3  779.62   323.2  792.53
   359.4  821.33   374.8  830.75   382.9  833.78   399.4  835.81   411.4  842.89
#Mann= 4 ,-1,0
       0     .06       0   150.2      .1       0  226.49    .045       0
  243.39      .1       0
Bank Sta=226.49,243.39
XS Rating Curve= 0 ,0
Exp/Cntr(USF)=0,0
Exp/Cntr=0.3,0.1

Type RM Length L Ch R = 1 ,1775    ,236.8,236.6,235.8
XS GIS Cut Line= 2
1626420.70008282555098.5519736821626216.14362605555379.397928668
#Sta/Elev= 30
       0  808.48     7.5   804.9    19.7   796.5    35.9  796.08    44.1  796.61
    48.1  795.83    52.2  793.33    61.1  786.64    65.8  784.13    68.4  783.18
    89.3  778.96      94  777.42   143.3  753.74  158.11745.7911   162.1   744.8
  167.59745.7911   186.1  757.67   198.3  763.74   206.7  768.91   212.7  771.56
   223.9   775.2   240.6  778.08   246.2  780.05   259.2  787.61   267.3  793.36
   284.2  804.07   290.7  807.17   303.8  811.96   328.8  824.12   347.4  831.83
#Mann= 4 ,-1,0
       0     .06       0  158.11    .045       0  167.59     .06       0
     260      .1       0
Bank Sta=158.11,167.59
XS Rating Curve= 0 ,0
Exp/Cntr(USF)=0,0
Exp/Cntr=0.3,0.1

Type RM Length L Ch R = 1 ,1538    ,163.6,160.2,155.6
XS GIS Cut Line= 6
1626236.62495273554907.4281080851626194.99084966554985.630051408
 1626160.4426904555052.5698781641626109.30795015555138.549036909
1626077.86542774555207.2106449941626062.39301774555296.312172834
#Sta/Elev= 30
       0  808.87    19.8  803.88      45  800.36    59.9  796.33    70.3  795.62
   104.4  790.66   108.1  788.57   119.1  778.24   122.8  776.53   137.6  776.51
   146.2  775.36   174.9  754.81   190.2  745.48  205.48739.8904   211.1   739.2
  216.19739.8899   227.9  745.42   242.2  756.92     247  759.18   266.3  760.49
   281.1  763.38   291.6  766.61   313.3     767   320.5  769.53   345.3   781.2
   355.3   784.7   375.2  794.62   388.6   797.8   411.9  808.84   429.9  813.29
#Mann= 5 ,-1,0
       0      .1       0  183.92     .06       0  205.48    .045       0
  216.19     .06       0  409.48      .1       0
Bank Sta=205.48,216.19
XS Rating Curve= 0 ,0
Exp/Cntr(USF)=0,0
Exp/Cntr=0.3,0.1

Type RM Length L Ch R = 1 ,1378    ,36.1,36.2,35.9
XS GIS Cut Line= 4
1626019.97063063554875.5519019611625987.27513139 555012.20232185
1626018.29393836555122.0256654421626004.88040021555264.544508271
#Sta/Elev= 30
       0  786.42     9.5  785.47    26.4  785.13    36.5   782.4    56.8  778.62
    63.5  776.15    73.6  770.91    83.8  766.85    90.5  763.36    97.2  760.92
   110.7  757.16   120.9  757.94   127.6  757.65     131  756.65   140.5  750.07
   154.7  737.39  158.92  735.07     165  734.19  168.57735.0671   175.2  738.38
   192.2  743.98   204.6  745.69   216.1  748.56   256.9  753.14   289.9  766.35
   306.4  774.38   326.1  780.54   342.6  788.12   365.7   797.6   397.8  805.55
#Mann= 5 ,-1,0
       0      .1       0     140     .06       0  158.92    .045       0
  168.57     .06       0  354.63      .1       0
Bank Sta=158.92,168.57
XS Rating Curve= 0 ,0
Exp/Cntr(USF)=0,0
Exp/Cntr=0.3,0.1

Type RM Length L Ch R = 1 ,1342    ,154.3,155.6,156.4
XS GIS Cut Line= 4
1625973.86159324554868.8451328871625949.54955535555013.879014119
1625984.76009299 555123.702357711625977.21497778555260.352777599
#Sta/Elev= 30
       0  788.15    22.9  784.27    49.5     777    59.5  773.39    69.4  768.48
    79.4  765.86    92.7   761.1   102.7   758.8     116   754.2     136  754.35
   142.6  750.33   145.9  749.08   159.7     747   163.1  745.85   166.6  742.69
     170  738.68  176.07734.1197   181.2  733.28  185.31734.1187   194.1  741.04
   205.4  744.64   211.4  745.72   242.4  747.15   279.5  757.33   286.4  760.39
   302.4  768.98   338.6  783.68   351.7  788.37   374.7  799.92   399.2  805.78
#Mann= 5 ,-1,0
       0      .1       0     140     .06       0  176.07    .045       0
  185.31     .06       0  352.39      .1       0
Bank Sta=176.07,185.31
XS Rating Curve= 0 ,0
Exp/Cntr(USF)=0,0
Exp/Cntr=0.3,0.1

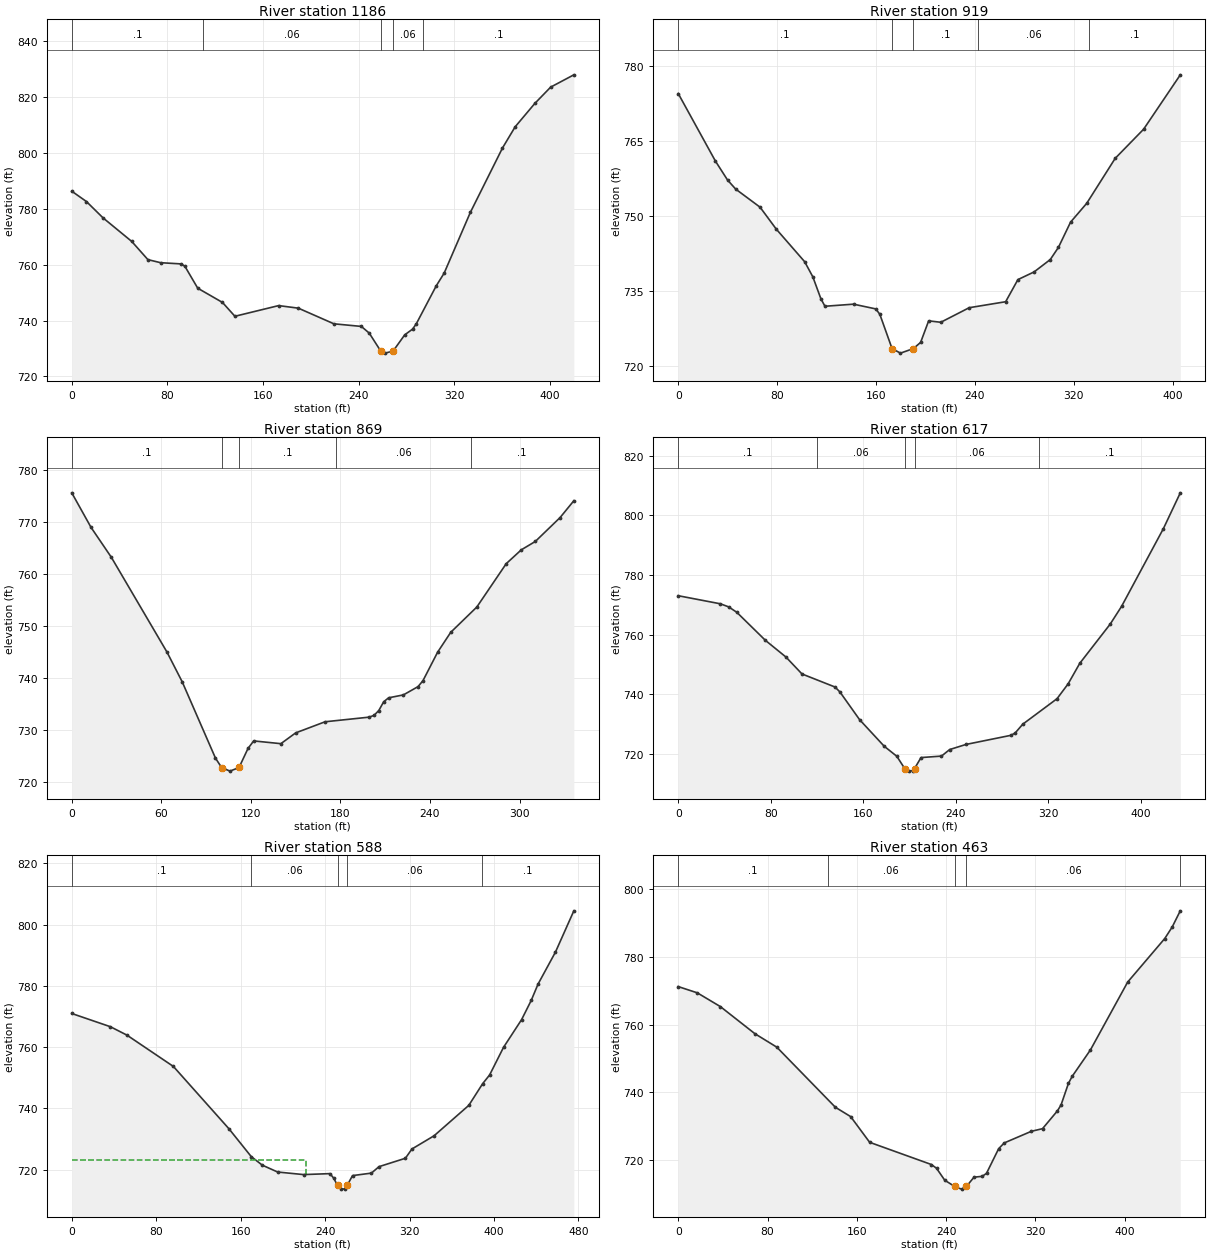
Type RM Length L Ch R = 1 ,1186    ,252.7,266.7,275.4
XS GIS Cut Line= 3
1625852.30140377554840.3413643211625807.86905866 554976.99178421
1625836.37282722555251.969316256
#Sta/Elev= 30
       0  786.27    12.3  782.56    26.1  776.75    50.2  768.29    63.7  761.79
    74.4  760.69    91.6  760.26    94.7  759.38   105.4  751.57   126.1  746.48
   136.5  741.53   173.1  745.35   189.6  744.43   219.3  738.84   242.3   737.9
   248.9  735.51  258.55  729.07   262.1  728.35  268.84729.0709   278.6  734.89
   285.2  736.95   288.3  738.86     305  752.44   311.6  756.97   333.5  778.68
   360.4  801.73     371   809.3   387.5  817.68   400.7  823.49   420.1  827.89
#Mann= 5 ,-1,0
       0      .1       0     110     .06       0  258.55    .045       0
  268.84     .06       0  293.69      .1       0
Bank Sta=258.55,268.84
XS Rating Curve= 0 ,0
Exp/Cntr(USF)=0,0
Exp/Cntr=0.3,0.1

Type RM Length L Ch R = 1 ,919     ,55.3,50.6,42.5
XS GIS Cut Line= 4
1625686.49834576554815.368792472 1625683.4425741554957.156597472
1625613.15982593554950.433899821 1625614.3821346555144.169823032
#Sta/Elev= 30
       0  774.58    30.1  761.04    39.9  757.25    46.5  755.43    66.2  751.81
    79.3  747.42   102.3  740.88   108.9  737.85   115.4  733.47   118.7  731.96
   141.8  732.38   159.8  731.43   163.1  730.35  172.99723.4752   179.8  722.57
  190.21723.4749   196.1  724.72   202.6  729.04   212.4  728.75   235.4  731.67
   264.9  732.87   274.8   737.3   287.9  738.84     301  741.32   307.6  743.76
   317.4  748.81   330.5  752.59   353.5  761.59   376.5  767.43   406.2  778.33
#Mann= 5 ,-1,0
       0      .1       0  172.99    .045       0  190.21      .1       0
  242.42     .06       0  332.42      .1       0
Bank Sta=172.99,190.21
XS Rating Curve= 0 ,0
Exp/Cntr(USF)=0,0
Exp/Cntr=0.3,0.1

Type RM Length L Ch R = 1 ,869     ,255.6,252.1,241.3
XS GIS Cut Line= 4
 1625654.7183205554816.5911011361625631.97618982 554902.22587737
1625602.97885454554927.6445396061625599.71443063 555136.83597105
#Sta/Elev= 30
       0  775.55    12.9  768.91    26.5  763.16    63.8  744.92      74   739.2
    96.3  724.52  100.39722.7258     106  722.03  112.08722.7282   118.1   726.4
   121.9  727.84   140.1  727.31     150  729.38   169.7  731.52   199.2  732.41
   202.5  732.75   205.7  733.68     209  735.37   212.3  736.13   222.2  736.69
     232  738.28   235.3  739.42   245.1  744.89   253.9  748.72   271.4  753.59
   291.1  761.93   301.2  764.59   310.6   766.2   327.2   770.8   336.4  774.03
#Mann= 5 ,-1,0
       0      .1       0  100.39    .045       0  112.08      .1       0
  177.16     .06       0  267.16      .1       0
Bank Sta=100.39,112.08
XS Rating Curve= 0 ,0
Exp/Cntr(USF)=0,0
Exp/Cntr=0.3,0.1

Type RM Length L Ch R = 1 ,617     ,29.2,29.1,29.1
XS GIS Cut Line= 4
  1625449.620661554801.8079904421625380.87627799554971.405413408
1625421.61990012555072.5099572031625414.07478491555214.358123125
#Sta/Elev= 30
       0  773.06    36.5  770.35    43.6  769.32    50.6  767.52    75.4   758.1
    93.1  752.53     107  746.85   135.6  742.47   139.8  740.82   156.8  731.54
   178.1  722.63     189  719.27  195.83715.1479   199.3   714.3   202.9   714.5
   204.3715.1489   209.9  718.84   227.6  719.34   234.7  721.53   248.8  723.24
   287.7   726.3   291.3  727.08   297.9  730.03   327.5  738.56   337.1  743.53
   347.2  750.43   373.5  763.56   383.3  769.48   419.5  795.56   434.1  807.53
#Mann= 5 ,-1,0
       0      .1       0     120     .06       0  195.83    .045       0
   204.3     .06       0  312.01      .1       0
Bank Sta=195.83,204.3
XS Rating Curve= 0 ,0
Exp/Cntr(USF)=0,0
Exp/Cntr=0.3,0.1

Type RM Length L Ch R = 1 ,588     ,120.1,124.8,128.5
XS GIS Cut Line= 4
1625403.51162362 554762.028466371625335.60558674554940.847696814
1625389.93041624555066.8511207971625383.89432408555213.980867364
#Sta/Elev= 30
       0     771    36.6  766.68    52.3  763.93    96.3   753.7   148.9  733.36
     170  724.28   180.5  721.47     195  719.23   219.6  718.39   244.6   718.7
   248.2  717.21   251.8  714.85   255.3  713.64   258.9  713.72  260.94714.8514
     266  718.06   283.9  718.87   291.1  720.98   316.1  723.72   322.3  726.75
   343.3  731.07   376.2  741.01   389.3  748.08   395.9  750.93   409.1  759.96
   426.2     769   435.3  775.26   441.8  780.61   458.3  791.07   475.7  804.53
#Mann= 5 ,-1,0
       0      .1       0     170     .06       0   251.8    .045       0
  260.94     .06       0  388.49      .1       0
#XS Ineff= 2 , 0
          222.02  723.13
Permanent Ineff=
       F       F
Bank Sta=251.8,260.94
XS Rating Curve= 0 ,0
Exp/Cntr(USF)=0,0
Exp/Cntr=0.3,0.1

Type RM Length L Ch R = 1 ,463     ,158.6,157.4,156.2
XS GIS Cut Line= 5
1625333.38092709 554730.677505841625296.22609296554848.842582162
1625272.83407938 554930.949701411625224.78233821555019.745783668
1625203.63704636 555157.77473751
#Sta/Elev= 30
       0  771.25    17.1   769.4    37.8  765.33    68.7  757.33    88.3  753.36
   140.8   735.6   154.5  732.84   171.5  725.25   226.8  718.69   231.4  717.59
   238.8  714.04  247.74   712.2   253.8  711.42   258.2  712.21     265  714.95
   272.4   715.2   276.2  716.09   287.1  723.37   292.1  725.07   316.4   728.5
   326.4  729.28   339.7  734.52     343  736.29   349.6  742.65   352.9   744.7
   369.3  752.53   402.7  772.59   435.9  785.44   442.6  788.86   449.8  793.63
#Mann= 5 ,-1,0
       0      .1       0  133.87     .06       0  247.74    .045       0
   258.2     .06       0  449.85      .1       0
Bank Sta=247.74,258.2
XS Rating Curve= 0 ,0
Exp/Cntr(USF)=0,0
Exp/Cntr=0.3,0.1

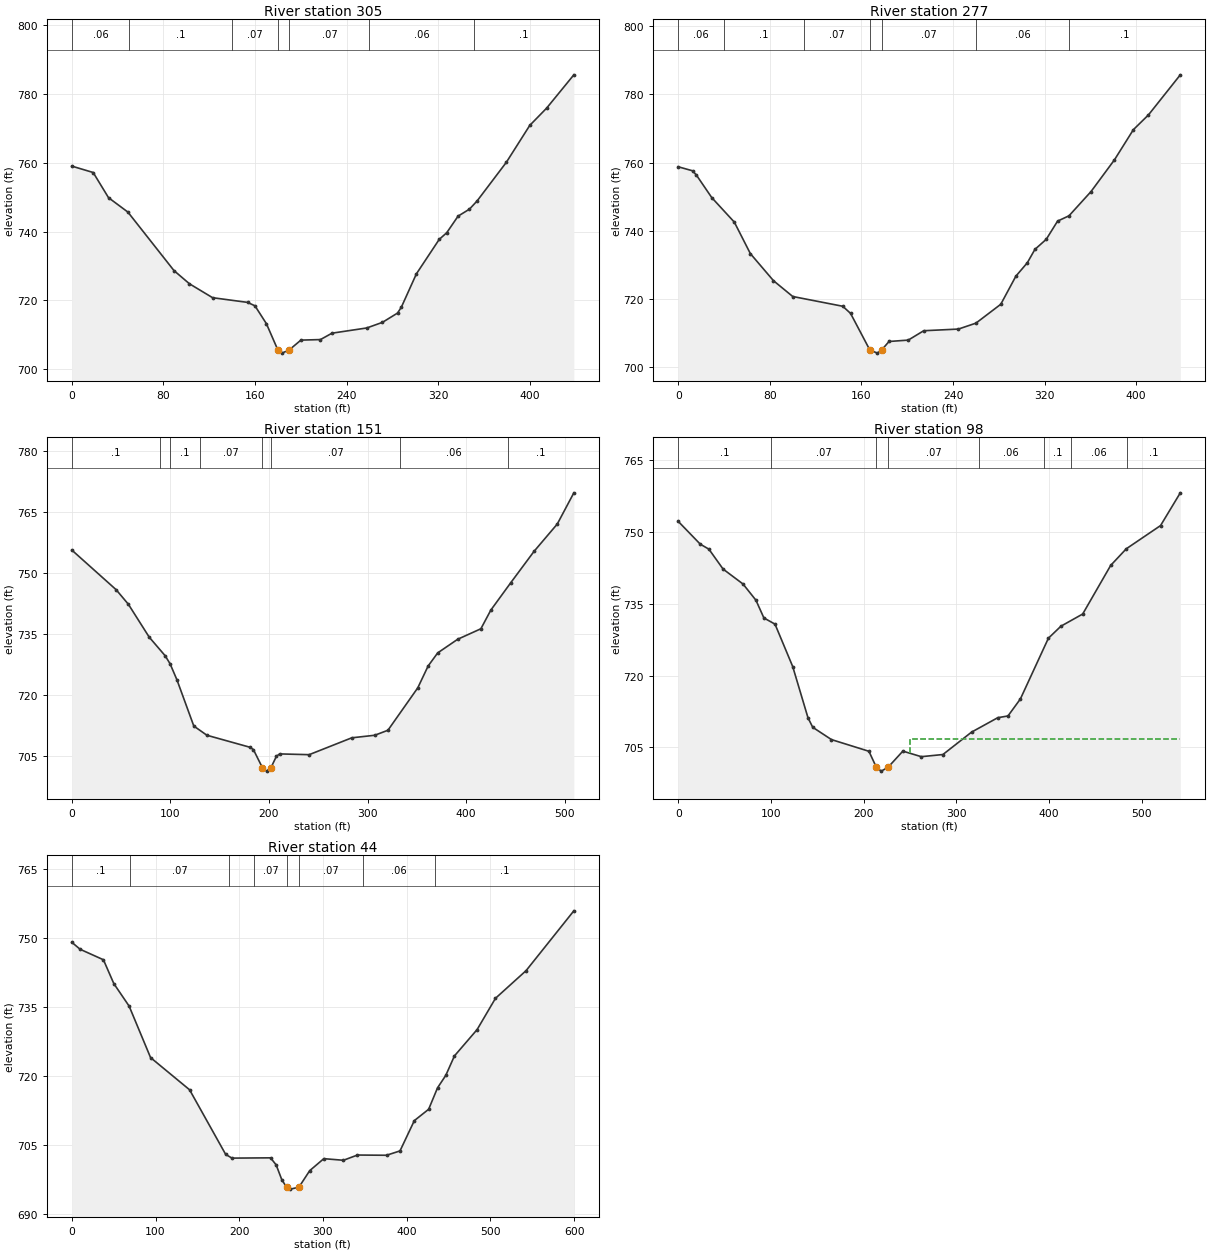
Type RM Length L Ch R = 1 ,305     ,28.5,28.5,28.5
XS GIS Cut Line= 3
 1625155.2803513554722.2604276411625092.65589507554996.902621233
1625113.02770613 555152.33199453
#Sta/Elev= 30
       0  759.02    18.7  757.16    32.1  749.84      49  745.66    89.3  728.64
   102.8  724.81     123  720.77   153.5  719.41     160  718.41     170  713.21
  179.97 705.595   183.6  704.66  189.94 705.597   200.1  708.44   217.2   708.6
   227.3  710.46   257.6  711.97   271.3   713.6   284.5   716.3   287.8  717.98
     301  727.71   320.9  737.71   327.5  739.66   337.4  744.48   347.3   746.5
     354  748.89   379.6  760.15     400  770.85   414.7  775.86   438.5  785.55
#Mann= 7 ,-1,0
       0     .06       0      50      .1       0     140     .07       0
  179.97    .045       0  189.94     .07       0     260     .06       0
  351.69      .1       0
Bank Sta=179.97,189.94
XS Rating Curve= 0 ,0
Exp/Cntr(USF)=0,0
Exp/Cntr=0.3,0.1

Type RM Length L Ch R = 1 ,277     ,126.1,126.1,125.7
XS GIS Cut Line= 3
1625124.72263471554728.2965198071625062.09817848  555002.9387134
1625082.46998954555158.368086696
#Sta/Elev= 30
       0  758.76    12.5  757.58    15.9  756.31    29.3  749.69      49  742.49
      63  733.24    83.2  725.28     100  720.64   143.7  717.77   150.5  715.68
  167.36704.9072     174     704  177.61704.9086   184.1  707.42   200.9  707.83
   214.4  710.58   244.7  711.07     260  712.81   281.7  718.36   294.9  726.62
   304.9  730.56   311.5  734.48   321.4  737.44   331.3  742.79   341.3  744.36
   360.5  751.47     381  760.81   397.5  769.66   410.7  774.01   438.5  785.78
#Mann= 7 ,-1,0
       0     .06       0      40      .1       0     110     .07       0
  167.36    .045       0  177.61     .07       0     260     .06       0
  341.69      .1       0
Bank Sta=167.36,177.61
XS Rating Curve= 0 ,0
Exp/Cntr(USF)=0,0
Exp/Cntr=0.3,0.1

Type RM Length L Ch R = 1 ,151     ,52.8,53.1,52.1
XS GIS Cut Line= 4
1625070.99094568554695.0894980861624972.51348339554822.249716379
1624948.61118672554972.3561394771624993.54750446 555163.57451285
#Sta/Elev= 30
       0  755.63      45  745.86    57.4  742.28    78.6  734.16    94.8  729.58
    99.7  727.63   106.7  723.66   123.8  712.29   137.1  710.02     181  707.05
   184.3  706.47  193.33  702.06   197.6  701.19  202.08  702.06   207.6  704.85
   210.9  705.43   240.8  705.24     284  709.39   307.3  710.02   320.7  711.25
     351   721.7   361.5  727.08   371.2   730.3   391.5  733.66     415  736.24
   425.1  740.84   445.4  747.61   468.9  755.29   492.5  762.03   509.3  769.71
#Mann= 8 ,-1,0
       0      .1       0      90     .07       0     100      .1       0
     130     .07       0  193.33    .045       0  202.08     .07       0
  332.83     .06       0  442.83      .1       0
Bank Sta=193.33,202.08
XS Rating Curve= 0 ,0
Exp/Cntr(USF)=0,0
Exp/Cntr=0.3,0.1

Type RM Length L Ch R = 1 ,98      ,53,53.9,53.9
XS GIS Cut Line= 4
1625053.78129207554679.7920282161624926.62107378554786.874317305
1624900.80659337554942.7172916041624947.65509485555154.969686047
#Sta/Elev= 30
       0  752.24    23.7  747.49    33.1  746.43    48.4  742.27    69.9  739.15
    83.8  735.77    92.4  732.06   104.4  730.76   123.5  721.89     140  711.17
   145.1   709.2   165.3  706.63   205.7  704.19   213.7  700.84     219  700.04
  226.32  700.84   242.3  704.22   262.2  703.06   285.5  703.51   316.4  708.19
   344.7  711.21   355.7  711.57   369.1  715.13   399.3  727.82   412.8  730.33
   436.3  732.88   466.5  743.04   483.3  746.51   520.3  751.37   541.6  758.21
#Mann= 8 ,-1,0
       0      .1       0     100     .07       0   213.7    .045       0
  226.32     .07       0  324.21     .06       0  394.21      .1       0
  424.21     .06       0  484.21      .1       0
#XS Ineff= 2 , 0
                          249.53          706.79
Permanent Ineff=
       F       F
Bank Sta=213.7,226.32
XS Rating Curve= 0 ,0
Exp/Cntr(USF)=0,0
Exp/Cntr=0.3,0.1

Type RM Length L Ch R = 1 ,44      ,,,
XS GIS Cut Line= 4
1625041.35209781554675.9676607491624881.68475604554754.367193831
1624844.39717323554936.9807404021624911.32360391555162.618420982
#Sta/Elev= 30
       0  749.16      10  747.63    37.8  745.35    50.2  740.17    68.5  735.26
    94.1  724.06   140.7  717.05   183.8  702.99   191.3  702.18   237.4  702.24
   244.1   700.7   250.8  697.49   256.5  695.85   261.1  695.43  271.25  695.85
   284.2  699.46     301  702.06   324.4  701.71   341.2  702.85   375.9   702.8
     392  703.75   409.1  710.34   426.2  712.81   436.8  717.47   446.7   720.2
     457  724.42   484.1  730.16     506  736.96   542.6  742.99   599.6     756
#Mann= 8 ,-1,0
       0      .1       0      70     .07       0  187.88     .08       0
  217.88     .07       0   256.5    .045       0  271.25     .07       0
  347.88     .06       0  434.26      .1       0
Bank Sta=256.5,271.25
XS Rating Curve= 0 ,0
Exp/Cntr(USF)=0,0
Exp/Cntr=0.3,0.1
LCMann Table=0

Chan Stop Cuts=-1
Use User Specified Reach Order=0
Composite Channel Slope=5